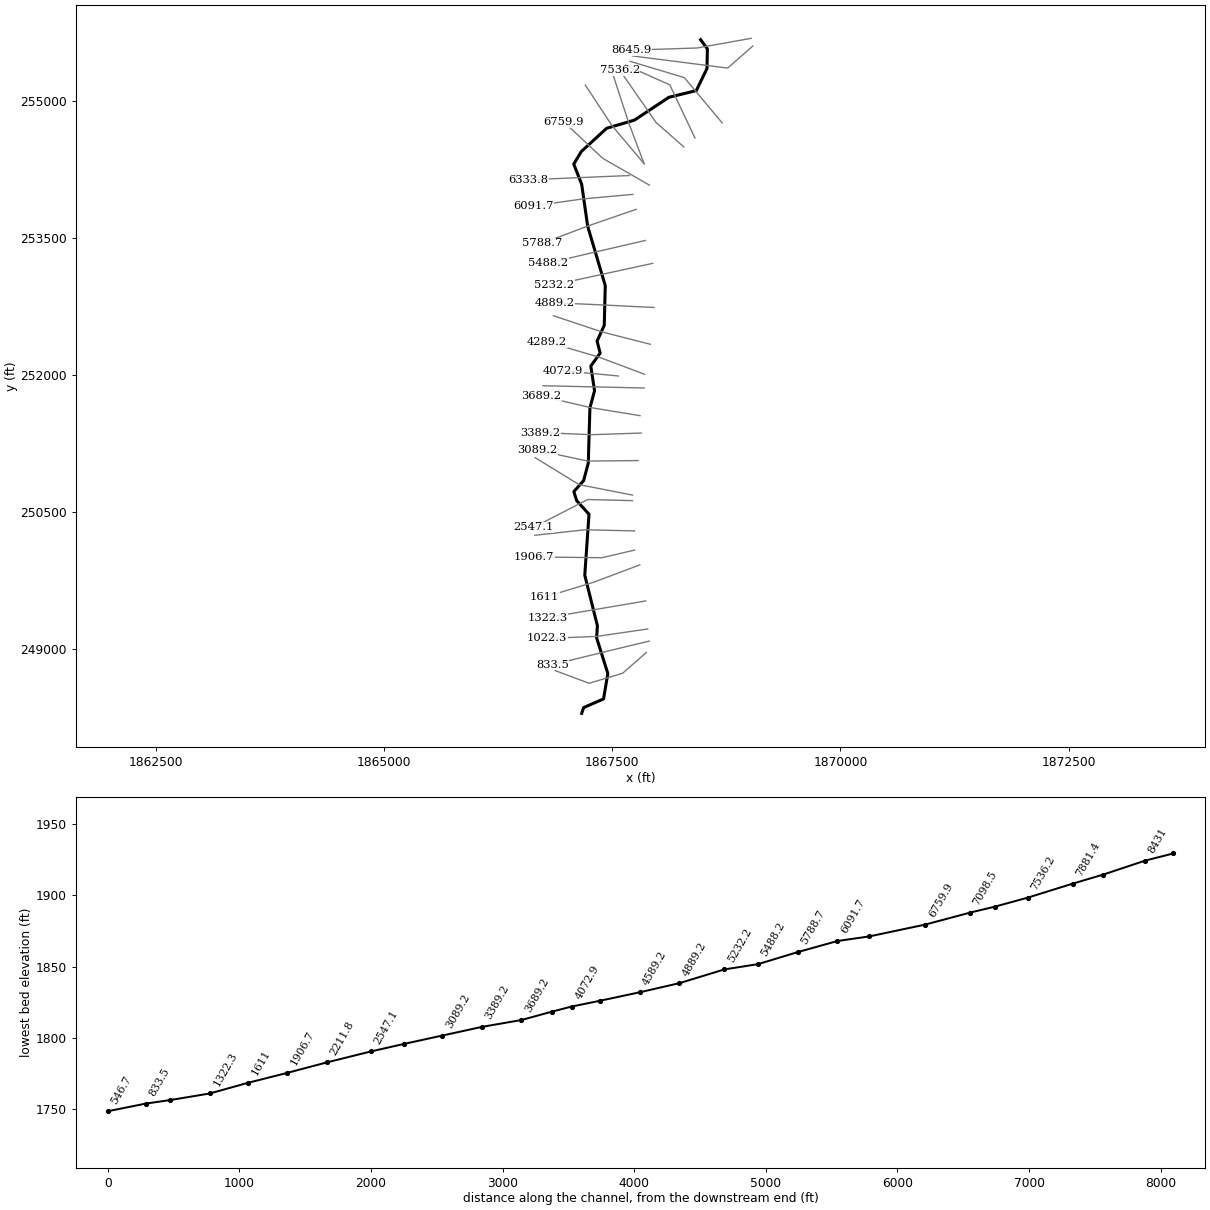
--- BrntFrk.prj (project) ---

Proj Title=BrntFrk
Current Plan=p01
Default Exp/Contr=0,0
English Units
Geom File=g01
Flow File=f01
Plan File=p01
BEGIN DESCRIPTION:
END DESCRIPTION:
DSS Export Rating Curves= 0
DSS Export Rating Curve Sorted= 0
DSS Export Volume Flow Curves= 0
DXF OffsetX= 0
DXF OffsetY= 0
DXF ScaleX= 0
DXF ScaleY= 0

--- BrntFrk.p01 (plan) ---

Plan Title=Floodplain
Program Version=4.00
Geom File=g01
Flow File=f01
K Sum by GR=0
Std Step Tol=0.01
Critical Tol=0.01
Num of Std Step Trials=20
Max Error Tol=0.3
Flow Tol Ratio=0.001
Split Flow NTrial=30
Split Flow Tol=0.02
Split Flow Ratio=0.02
Log Output Level=0
Friction Slope Method=1
Unsteady Friction Slope Method=2
Unsteady Bridges Friction Slope Method=1
Global Log Level=0
CheckData=False
Run HTab=0
Run UNet=0
Run PostProcess=0
UNET Theta=0
UNET Theta Warmup=0
UNET ZTol=0
UNET ZSATol=0
UNET MxIter=0
UNET MaxInSteps=0
UNET DtIC=0
UNET DtMin=0
UNET MaxCRTS=0
UNET WFStab=0
UNET SFStab=0
UNET WFX=0
UNET SFX=0
UNET DSS MLevel=0
UNET DZMax Abort=0
UNET Convert EG Bridges=0
UNET Use Existing IB Tables=0
UNET Froude Limit=0
UNET Froude Power=0
Write IC File=0
Echo Input=False
Echo Output=False
Write Detailed=0

--- BrntFrk.f01 (steady flow) ---

Flow Title=NFF Regression Equation
Program Version=4.00
Number of Profiles=1
Profile Names=P100yr
River Rch & RM=BrntFrk,Main      ,8645.9
909.5346
River Rch & RM=BrntFrk,Main      ,6759.9
956.3408
River Rch & RM=BrntFrk,Main      ,6333.8
1260.689
River Rch & RM=BrntFrk,Main      ,4889.2
1285.856
River Rch & RM=BrntFrk,Main      ,546.7
1427.435
Boundary for River Rch & Prof#=BrntFrk,Main      ,1
Up Type=0
Dn Type=3
Dn Slope=0.016883

--- BrntFrk.g01 (geometry) ---

Geom Title=USGS 3m DEM
Program Version=4.10

River Reach=BrntFrk         ,Main
Reach XY= 30
     1868468.508      255674.638     1868543.171      255573.811
     1868538.634      255358.854     1868421.942      255116.385
     1868121.353      255043.107     1867744.495      254793.364
     1867439.885       254703.76     1867161.829      254448.855
     1867079.369      254311.015     1867166.327      254090.276
     1867231.737      253631.092     1867424.521      252980.445
     1867413.547      252545.249     1867334.984      252372.947
     1867368.514       252240.86      1867266.07      252099.696
     1867307.179      251828.968     1867256.487      251641.049
     1867238.458      251035.882      1867187.21      250843.961
     1867080.507      250724.195     1867111.114      250625.881
     1867246.504      250475.947     1867200.093      249808.499
     1867338.382      249255.084     1867330.071      249122.079
     1867452.805      248731.511     1867405.821      248453.347
     1867187.469      248358.186      1867166.54         248295.

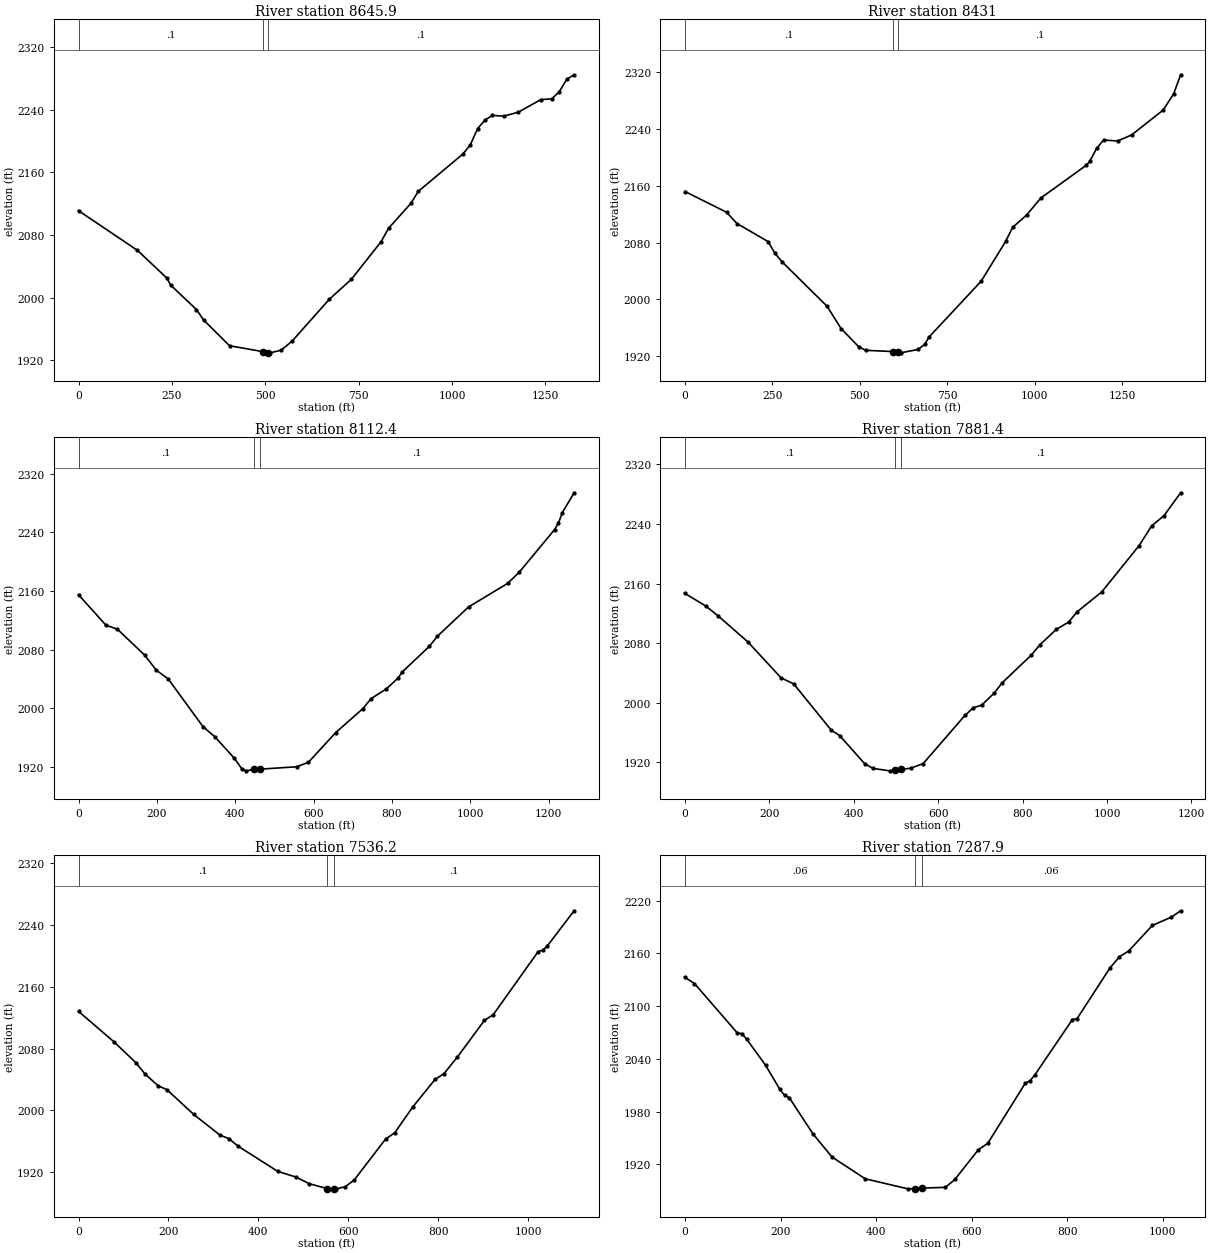
Type RM Length L Ch R = 1 ,8645.9  ,221,213.9,206.7
XS GIS Cut Line= 3
      1869023.12        255688.9     1868430.915       255583.22
     1867706.233      255559.378
#Sta/Elev= 30
       0 2111.18   157.8 2060.46   236.7 2024.91   246.5 2016.18   315.6 1984.83
   335.3  1971.3   404.3 1938.56   492.7 1931.13   507.7 1929.72   512.8  1929.5
   542.4 1932.87     572  1944.6   671.1 1997.86   730.7 2023.63   810.1 2071.68
     830 2088.72   889.6 2120.48   909.5 2135.88  1028.7 2183.52  1048.5 2195.19
  1068.4 2216.11  1088.2 2227.11  1108.1 2233.07  1137.9  2231.9  1177.6 2237.18
  1237.2 2253.07    1267 2254.16  1286.9 2263.22  1306.8 2278.98  1326.6 2284.89
#Mann= 3 , 0 , 0
       0      .1       0   492.7    .045       0   507.7      .1       0
Bank Sta=492.7,507.7
XS Rating Curve= 0 ,0
Exp/Cntr=0.3,0.1

Type RM Length L Ch R = 1 ,8431    ,335.3,318.4,301.5
XS GIS Cut Line= 3
      1869041.05       255604.92       1868765.9      255363.137
     1867723.644      255495.851
#Sta/Elev= 30
       0 2151.91   118.8 2122.65   148.5 2106.77   237.6 2081.29   257.4 2064.63
   277.2  2052.9   406.3    1990   446.3 1958.63   496.4 1933.09   516.4 1928.05
   594.8 1926.24   609.8 1925.08   616.4 1924.47   666.5 1929.25   686.5 1937.09
   696.5 1946.15   846.6 2025.43   916.6 2081.57   936.6 2101.37   976.7 2118.79
  1016.7 2142.53  1146.8 2188.77  1156.8 2194.26  1176.8 2212.78  1196.8 2224.53
  1236.8 2223.16  1276.9 2231.72  1366.9 2266.73    1397 2289.59    1417 2316.52
#Mann= 3 , 0 , 0
       0      .1       0   594.8    .045       0   609.8      .1       0
Bank Sta=594.8,609.8
XS Rating Curve= 0 ,0
Exp/Cntr=0.3,0.1

Type RM Length L Ch R = 1 ,8112.4  ,236.1,230.5,224.9
XS GIS Cut Line= 3
     1868705.386      254762.559     1868290.624      255258.582
      1867698.12      255436.689
#Sta/Elev= 30
       0 2154.97    69.6 2113.72    99.5 2107.85   169.1 2072.51     199 2051.83
   228.8 2040.24   318.3 1974.66   348.2 1961.17   397.9 1931.82   417.8 1916.87
   427.7 1914.68   448.3 1916.58   463.3 1916.96     557 1920.23   586.9 1926.29
   656.6 1966.84   726.4 1999.75   746.4    2013   786.3 2026.68   816.2 2041.46
   826.2 2049.43     896 2084.76     916 2098.23   995.8 2138.37  1095.6 2170.46
  1125.6 2186.05  1215.4 2243.88  1225.4  2252.9  1235.3 2267.12  1265.3 2294.16
#Mann= 3 , 0 , 0
       0      .1       0   448.3    .045       0   463.3      .1       0
Bank Sta=448.3,463.3
XS Rating Curve= 0 ,0
Exp/Cntr=0.3,0.1

Type RM Length L Ch R = 1 ,7881.4  ,342,345.6,349.2
XS GIS Cut Line= 3
     1868407.021      254597.164     1868131.613      255179.076
     1867647.173      255395.734
#Sta/Elev= 30
       0 2146.68    49.5 2129.69    79.2 2116.18   148.6 2081.74   227.8  2033.2
   257.5 2025.22   346.7 1962.88   366.5 1955.71   425.9 1917.86   445.7 1911.56
   485.3 1908.37   497.2 1909.06   512.2 1910.33   534.8 1911.88   564.6 1918.22
   663.4 1982.89   683.1 1993.09   702.8 1996.63   732.2 2012.51   751.9 2026.86
   820.7 2063.92   840.3 2077.35   879.6 2098.29   909.1 2108.24   928.8 2121.84
   987.8 2148.91  1076.2 2211.09  1105.7 2237.48  1135.2  2251.3  1174.5 2281.98
#Mann= 3 , 0 , 0
       0      .1       0   497.2    .045       0   512.2      .1       0
Bank Sta=497.2,512.2
XS Rating Curve= 0 ,0
Exp/Cntr=0.3,0.1

Type RM Length L Ch R = 1 ,7536.2  ,255,248.4,241.8
XS GIS Cut Line= 3
     1868284.924      254499.444     1867982.095      254766.122
      1867583.06      255339.674
#Sta/Elev= 30
       0  2128.1    78.7 2088.76   127.9 2061.53   147.6 2047.28   177.2 2031.71
   196.8  2026.7   255.9 1994.85   314.9 1967.82   334.6 1963.48   354.3 1953.88
   443.4 1920.92   483.4 1913.73   513.3 1905.02   553.7 1898.72   568.7 1898.44
   573.2 1898.43   593.2 1901.14   613.1 1909.86     683 1962.91     703 1970.77
   742.9 2004.01   792.8 2039.94   812.8 2047.53   842.7 2069.02   902.6 2116.29
   922.6 2123.97  1022.4 2205.55  1032.4 2207.11  1042.3  2212.5  1102.2 2258.25
#Mann= 3 , 0 , 0
       0      .1       0   553.7    .045       0   568.7      .1       0
Bank Sta=553.7,568.7
XS Rating Curve= 0 ,0
Exp/Cntr=0.3,0.1

Type RM Length L Ch R = 1 ,7287.9  ,179.8,189.1,195.6
XS GIS Cut Line= 3
     1867850.411      254314.836     1867685.816      254751.188
     1867508.217      255294.186
#Sta/Elev= 30
       0 2132.57    19.8 2125.59   109.2 2069.58   119.1 2068.52     129  2062.4
   168.7 2032.62   198.4 2005.37   208.4 1998.46   218.3 1995.82   267.9 1954.67
   307.6  1928.4   377.1 1903.64   466.4 1892.16   481.3 1892.54   496.3 1893.02
   545.2 1893.85   564.9 1902.79   614.1 1936.59   633.8 1943.85   712.6 2012.43
   722.5 2015.14   732.3 2021.61   811.1 2084.64     821 2085.78   889.9 2143.48
   909.6 2155.98   929.3  2162.8   978.6 2191.75    1018 2201.03  1037.7 2208.34
#Mann= 3 , 0 , 0
       0     .06       0   481.3    .045       0   496.3     .06       0
Bank Sta=481.3,496.3
XS Rating Curve= 0 ,0
Exp/Cntr=0.3,0.1

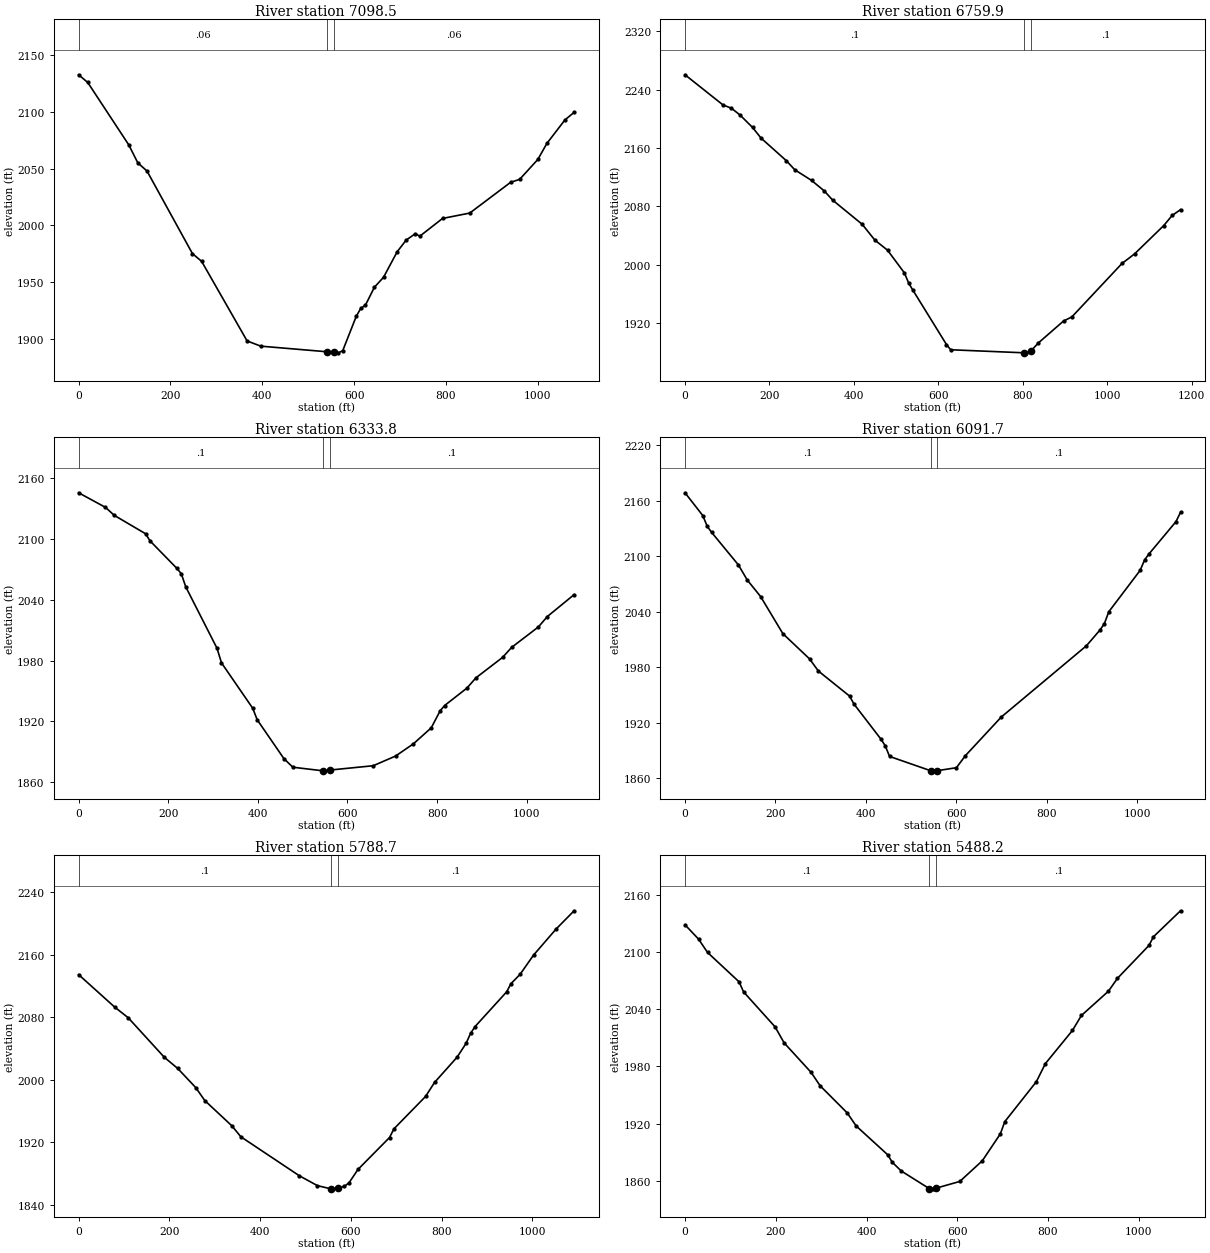
Type RM Length L Ch R = 1 ,7098.5  ,336.2,338.7,344
XS GIS Cut Line= 3
     1867850.411      254314.836     1867498.939      254731.942
       1867205.5       255177.57
#Sta/Elev= 30
       0 2132.57    19.8 2125.83   109.1 2070.96   128.9 2055.06   148.8 2047.95
   247.9 1975.21   267.8 1968.48   366.9 1898.42   396.7 1893.84   540.4 1888.92
   555.4 1888.44   565.2 1887.96   575.1 1889.82   604.7 1920.18   614.6 1927.21
   624.5 1929.84   644.2 1945.75     664 1954.42   693.7 1976.88   713.4  1987.2
   733.2 1992.73   743.1  1990.6   792.5 2006.19   851.8 2010.92   940.7 2037.96
   960.4 2040.57    1000 2058.08  1019.7 2072.18  1059.2 2092.95    1079 2099.49
#Mann= 3 , 0 , 0
       0     .06       0   540.4    .045       0   555.4     .06       0
Bank Sta=540.4,555.4
XS Rating Curve= 0 ,0
Exp/Cntr=0.3,0.1

Type RM Length L Ch R = 1 ,6759.9  ,407.2,425.5,443.9
XS GIS Cut Line= 3
      1867908.31       254080.98     1867397.077      254374.528
      1866970.35      254773.202
#Sta/Elev= 30
       0 2260.16    89.9 2218.89   109.9 2214.37   129.9 2205.27   159.9 2188.11
   179.8 2173.64   239.8 2142.65   259.8 2130.22   299.8 2115.52   329.7 2101.25
   349.7 2088.57   419.7 2055.48   449.6  2033.9   479.6 2020.13   519.6 1988.99
   529.6 1975.19   539.6 1965.44   619.2 1891.01   629.1 1883.83   803.5 1879.64
   807.3 1879.61   818.5 1881.67     837 1893.24   896.4 1923.12   916.2 1928.78
  1034.9  2001.9  1064.6 2014.96  1133.9 2053.84  1153.7 2067.64  1173.5 2075.55
#Mann= 3 , 0 , 0
       0      .1       0   803.5    .045       0   818.5      .1       0
Bank Sta=803.5,818.5
XS Rating Curve= 0 ,0
Exp/Cntr=0.3,0.1

Type RM Length L Ch R = 1 ,6333.8  ,241.2,242.5,244.8
XS GIS Cut Line= 2
     1867687.004      254186.043     1866582.302      254139.898
#Sta/Elev= 30
       0 2145.29    59.8 2130.94    79.7    2123   149.4 2104.91   159.4 2097.87
   219.1 2070.87   229.1 2065.55   239.1 2052.57   308.8 1992.08   318.8 1977.69
   388.5 1932.97   398.4 1921.69   458.2 1883.27   478.1 1874.86   545.3 1871.33
   547.8  1871.3   560.3 1872.05   657.4 1876.33   707.2 1885.85   747.1 1897.92
   786.9 1913.68   806.8  1930.5   816.8 1935.67   866.6 1952.87   886.5  1962.9
   946.3 1983.16   966.2 1992.91    1026 2013.09  1045.9 2023.33  1105.7 2044.93
#Mann= 3 , 0 , 0
       0      .1       0   545.3    .045       0   560.3      .1       0
Bank Sta=545.3,560.3
XS Rating Curve= 0 ,0
Exp/Cntr=0.3,0.1

Type RM Length L Ch R = 1 ,6091.7  ,297,303,308
XS GIS Cut Line= 3
     1867728.073       253979.98     1867179.607      253929.935
     1866639.759      253853.994
#Sta/Elev= 30
       0 2168.85    39.3 2144.18    49.2 2132.49      59 2125.91     118 2090.85
   137.7 2074.44   167.2  2056.6   216.4 2016.47   275.4 1989.17     295 1976.01
   363.9 1948.95   373.7  1940.3   432.7 1902.74   442.6  1895.4   452.4 1883.65
   543.2  1868.2   550.7 1868.06   558.2 1868.26   600.3 1871.45   620.1 1884.47
   699.4 1926.21   887.8 2003.34   917.5 2020.22   927.4 2027.17   937.3 2040.15
  1006.7 2084.97  1016.6 2096.37  1026.5 2102.87    1086 2137.72  1095.9 2147.68
#Mann= 3 , 0 , 0
       0      .1       0   543.2    .045       0   558.2      .1       0
Bank Sta=543.2,558.2
XS Rating Curve= 0 ,0
Exp/Cntr=0.3,0.1

Type RM Length L Ch R = 1 ,5788.7  ,303.4,300.5,297.4
XS GIS Cut Line= 3
     1867764.104      253816.356     1867247.603      253638.383
     1866737.048      253445.015
#Sta/Elev= 30
       0 2134.57    79.5 2092.98   109.3 2079.33   188.7 2028.83   218.5 2014.38
   258.2 1989.88   278.1 1973.34   337.7 1941.01   357.6 1926.92   486.7 1876.94
   526.4 1864.36   556.1 1860.26   571.1 1860.86     586 1863.55   595.9 1867.86
   615.8  1885.1   685.3 1925.98   695.2 1937.18   764.7 1978.51   784.5 1996.45
   834.2 2028.82     854 2046.45   863.9 2059.22   873.9 2068.08   943.4 2112.44
   953.3 2123.16   973.1  2134.9  1002.9 2159.65  1052.5 2192.95  1092.2 2216.32
#Mann= 3 , 0 , 0
       0      .1       0   556.1    .045       0   571.1      .1       0
Bank Sta=556.1,571.1
XS Rating Curve= 0 ,0
Exp/Cntr=0.3,0.1

Type RM Length L Ch R = 1 ,5488.2  ,256.3,256,255.7
XS GIS Cut Line= 3
     1867864.266      253475.171     1867332.353      253351.945
      1866800.44      253228.719
#Sta/Elev= 30
       0 2128.27    29.8 2113.33    49.6 2099.35   119.1 2068.59     129 2058.07
   198.6 2021.35   218.4 2004.67     278 1973.71   297.8 1959.73   357.4 1931.38
   377.2 1917.67   446.7  1887.5   456.6 1879.74   476.5 1870.55   538.5 1852.04
     546 1851.84   553.5 1852.56   605.6 1859.59   655.2 1881.23   694.9 1909.35
   704.8 1922.23   774.3 1964.02   794.2 1982.97   853.8 2017.64   873.6 2033.34
   933.2 2058.78     953  2072.2  1022.5 2106.66  1032.4 2115.79    1092 2142.97
#Mann= 3 , 0 , 0
       0      .1       0   538.5    .045       0   553.5      .1       0
Bank Sta=538.5,553.5
XS Rating Curve= 0 ,0
Exp/Cntr=0.3,0.1

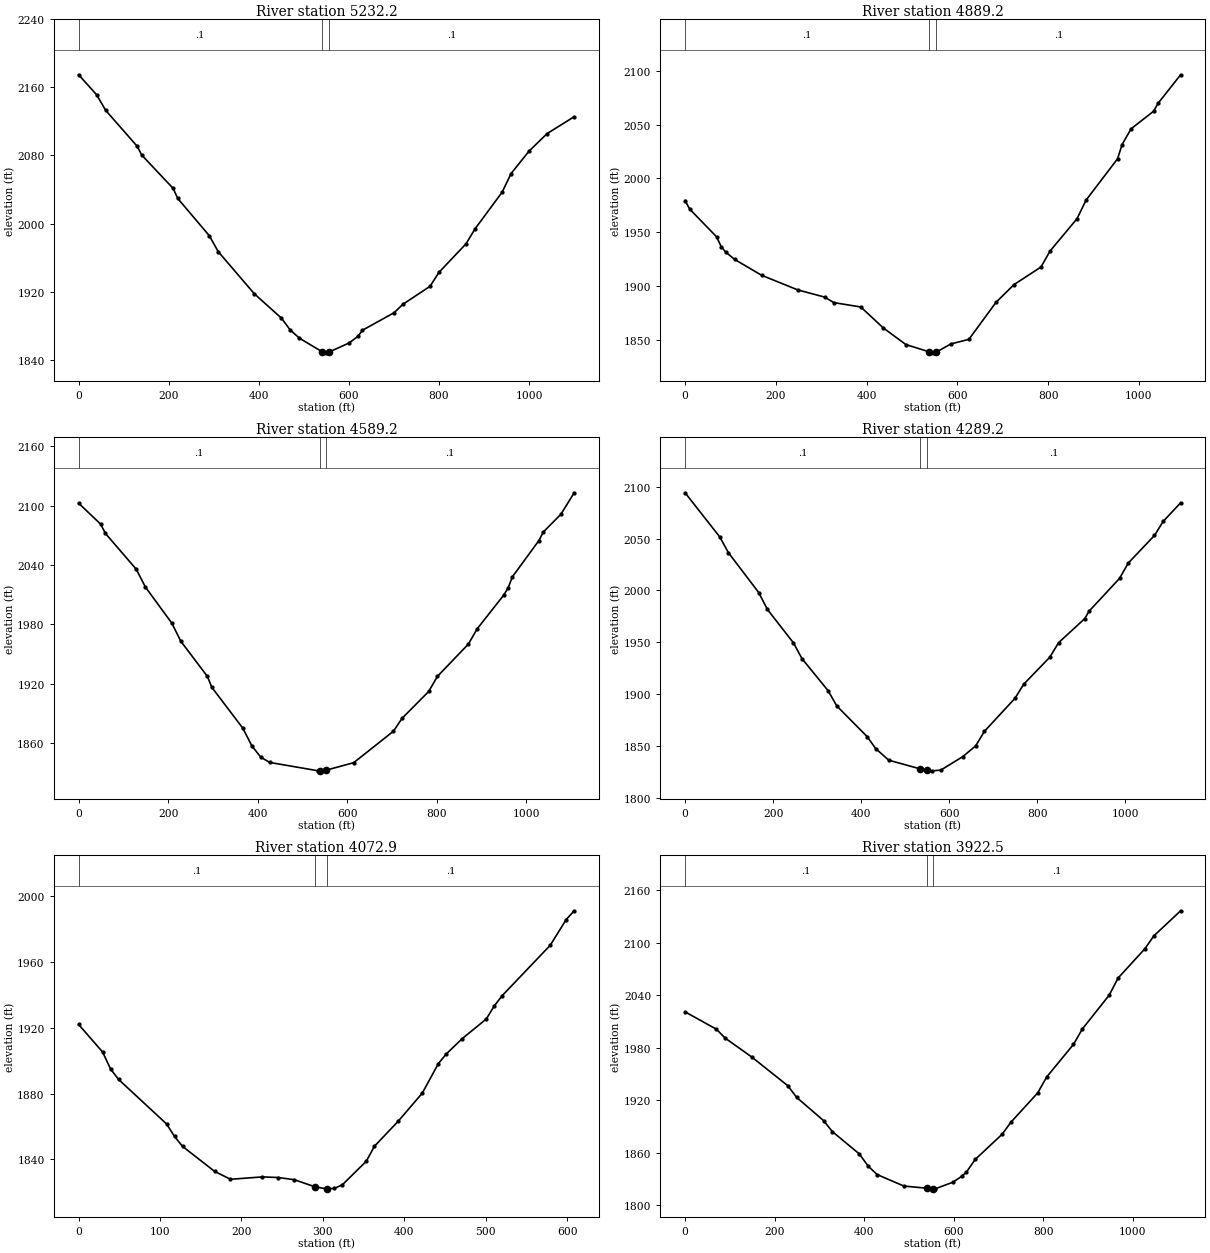
Type RM Length L Ch R = 1 ,5232.2  ,349.1,343,337
XS GIS Cut Line= 2
     1867944.087      253224.302     1866869.054      252990.429
#Sta/Elev= 30
       0  2174.8      40 2151.32      60    2133     130  2090.8     140 2080.55
     210 2041.22     220 2029.53     290 1985.81     310 1966.96   390.1  1917.5
   450.1 1888.95   470.1 1874.79   490.1 1865.39   540.3 1849.47   550.1 1848.13
   555.3 1848.89   600.1 1859.63   620.1 1867.48   630.1 1874.67   700.1 1895.18
   720.1 1905.24   780.1 1926.23   800.1 1942.71   860.1 1976.25   880.1  1993.8
   940.2 2036.82   960.2 2058.82  1000.2 2085.22  1040.2 2105.74  1100.2 2125.52
#Mann= 3 , 0 , 0
       0      .1       0   540.3    .045       0   555.3      .1       0
Bank Sta=540.3,555.3
XS Rating Curve= 0 ,0
Exp/Cntr=0.3,0.1

Type RM Length L Ch R = 1 ,4889.2  ,304.5,300,293.7
XS GIS Cut Line= 3
     1867959.138      252740.743     1867413.812      252767.839
     1866868.349      252792.237
#Sta/Elev= 30
       0 1979.57     9.9 1971.72    69.5  1945.9    79.4 1936.98    89.4 1931.81
   109.2 1925.01   168.8 1910.28   248.2 1896.78   307.7 1890.07   327.6    1885
   387.2 1880.94   436.8 1861.52   486.4 1846.17   538.5 1839.31     546 1838.46
   553.5 1839.16   585.7 1846.69   625.4 1850.97     685 1885.17   724.7 1901.66
   784.3 1917.98   804.1 1932.71   863.7 1962.76   883.5  1979.9     953 2018.24
     963 2031.45   982.8 2046.03  1032.4 2062.28  1042.4 2069.73    1092 2096.08
#Mann= 3 , 0 , 0
       0      .1       0   538.5    .045       0   553.5      .1       0
Bank Sta=538.5,553.5
XS Rating Curve= 0 ,0
Exp/Cntr=0.3,0.1

Type RM Length L Ch R = 1 ,4589.2  ,302.6,300,301
XS GIS Cut Line= 3
     1867917.602      252338.106     1867388.659      252473.147
     1866855.917       252651.04
#Sta/Elev= 30
       0 2102.51    49.6 2081.14    59.6  2072.1     129 2035.66   148.9 2018.02
   208.4 1981.24   228.3  1963.1   287.8 1927.51   297.8 1916.44   367.2 1875.04
   387.1 1857.41     407 1845.96   426.8 1840.61     536 1832.11   538.4 1832.12
   553.4  1832.8   614.9 1840.36   703.6 1872.14   723.3 1885.35   782.4 1912.28
   802.1 1927.62   871.1 1960.12   890.8 1975.61   949.9 2009.47   959.8 2016.74
   969.6 2028.19  1028.7 2064.71  1038.6 2073.36    1078 2091.36  1107.6 2113.02
#Mann= 3 , 0 , 0
       0      .1       0   538.4    .045       0   553.4      .1       0
Bank Sta=538.4,553.4
XS Rating Curve= 0 ,0
Exp/Cntr=0.3,0.1

Type RM Length L Ch R = 1 ,4289.2  ,210.3,216.3,220.5
XS GIS Cut Line= 3
     1867856.639      252008.764     1867349.713      252198.956
     1866788.705      252363.106
#Sta/Elev= 30
       0 2094.13    78.8 2051.57    98.4 2036.43   167.4 1997.92     187 1981.73
   246.1 1949.57   265.8 1934.17   324.9 1903.48   344.6 1888.76   413.5 1859.24
   433.1 1847.63   462.7 1836.45   533.9 1828.11   548.9 1826.83   561.2 1826.19
   581.1  1826.9   630.6 1839.78   660.3 1850.23   680.1 1864.25   749.5 1896.02
   769.3 1909.61   828.7 1935.67   848.6 1949.65     908 1972.81   917.9 1979.99
   987.3 2011.71  1007.1 2026.46  1066.5 2052.97  1086.3 2066.55    1126 2084.45
#Mann= 3 , 0 , 0
       0      .1       0   533.9    .045       0   548.9      .1       0
Bank Sta=533.9,548.9
XS Rating Curve= 0 ,0
Exp/Cntr=0.3,0.1

Type RM Length L Ch R = 1 ,4072.9  ,148.6,150.4,152.2
XS GIS Cut Line= 3
     1867568.746      251990.352     1867402.615      252006.174
     1866962.763      252047.311
#Sta/Elev= 30
       0 1921.96    29.4 1905.27    39.3 1894.87    49.1 1888.56     108 1861.54
   117.8 1853.92   127.6 1847.92   166.9 1832.76   186.5 1827.92   225.8 1829.38
   245.4 1828.99     265 1827.65   290.3 1823.34   304.3 1822.12   305.3 1822.14
   314.1 1822.36     324 1824.62   353.4 1838.96   363.2 1847.95   392.7 1863.31
   422.1 1880.29   441.8 1898.19   451.6  1904.1   471.2 1913.41   500.7 1925.31
   510.5 1933.28   520.3 1939.54   579.2 1970.08   598.8 1985.71   608.6 1991.04
#Mann= 3 , 0 , 0
       0      .1       0   290.3    .045       0   305.3      .1       0
Bank Sta=290.3,305.3
XS Rating Curve= 0 ,0
Exp/Cntr=0.3,0.1

Type RM Length L Ch R = 1 ,3922.5  ,236.3,233.2,228.6
XS GIS Cut Line= 2
     1867850.377      251859.029     1866743.692      251883.642
#Sta/Elev= 30
       0 2020.91    69.8 2001.11    89.8  1990.8   149.6    1969   229.4 1936.46
   249.3 1923.05   309.2 1896.63   329.1 1883.89   388.9 1858.59   408.9 1844.57
   428.8 1834.89   488.7 1821.71   539.8 1819.23   554.8 1818.57   558.5 1818.52
   598.4 1826.12   618.3 1832.95   628.3  1837.6   648.2 1852.19     708 1880.83
     728 1894.76   787.8 1928.32   807.8 1946.47   867.6 1983.69   887.6 2001.42
   947.4 2040.02   967.3 2059.59  1027.2 2093.12  1047.1 2107.76    1107  2136.5
#Mann= 3 , 0 , 0
       0      .1       0   539.8    .045       0   554.8      .1       0
Bank Sta=539.8,554.8
XS Rating Curve= 0 ,0
Exp/Cntr=0.3,0.1

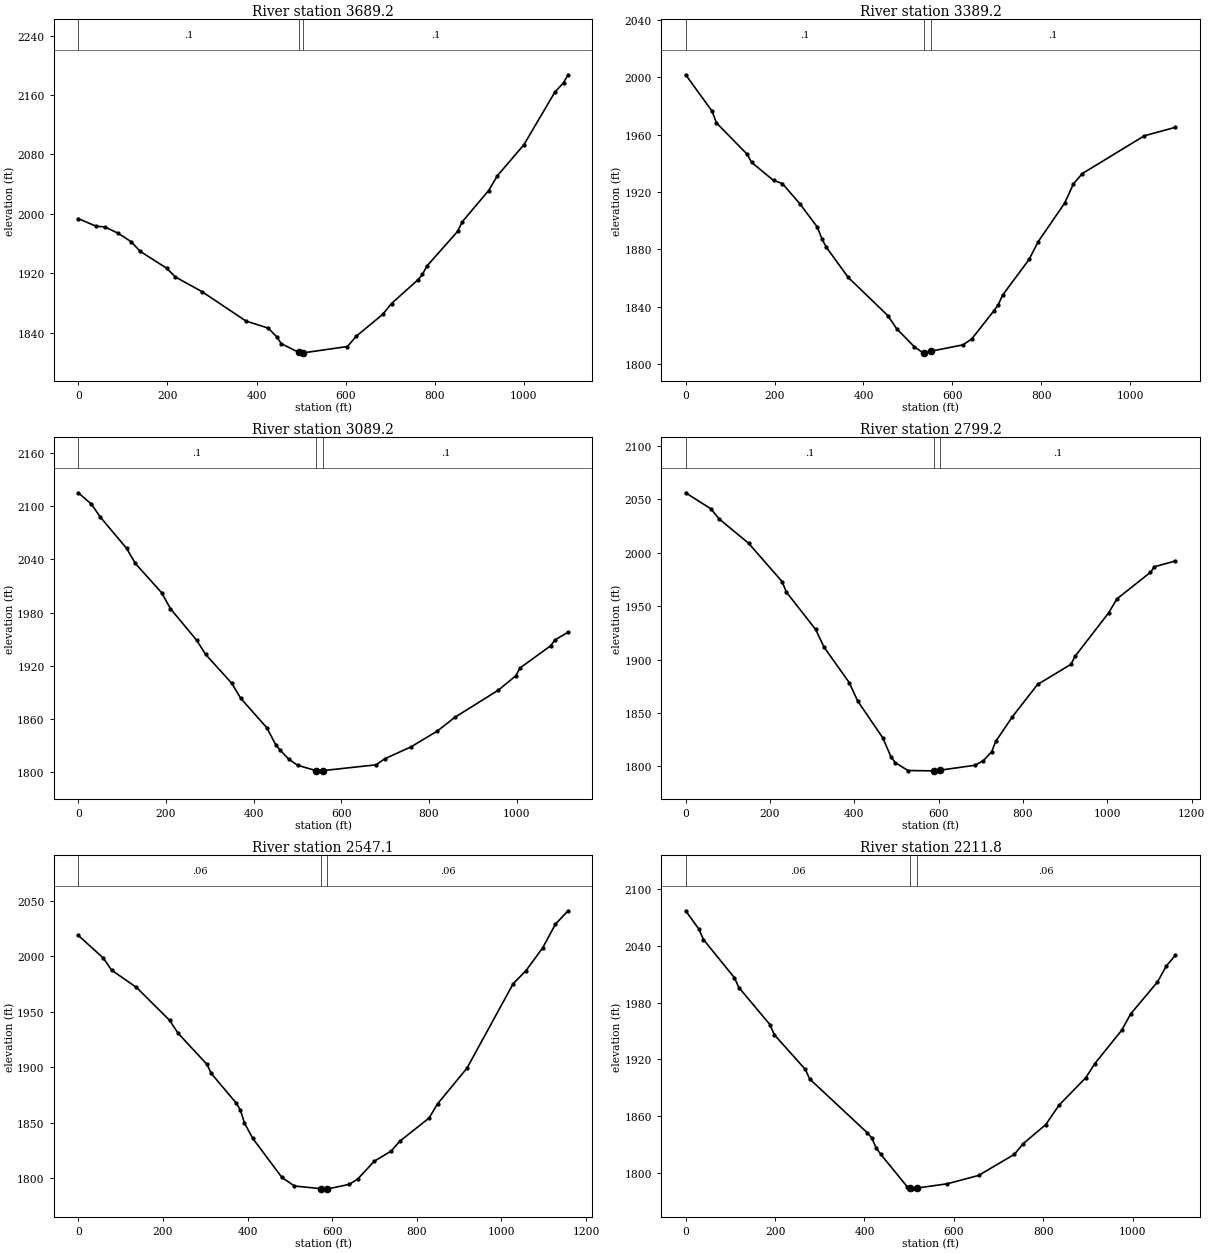
Type RM Length L Ch R = 1 ,3689.2  ,295.6,300,304.3
XS GIS Cut Line= 3
     1867805.365      251555.873     1867258.062      251645.373
     1866727.691      251769.038
#Sta/Elev= 30
       0 1993.51    39.6 1983.41    59.4  1982.3    89.1 1973.98   118.8  1962.3
   138.6 1949.56   198.1 1926.76   217.9 1914.87   277.3 1895.25   376.3 1855.48
   425.8 1846.05   445.6 1834.19   455.5 1825.01   495.2 1813.13   505.1 1812.63
   604.1 1821.16   623.9 1835.03   683.3 1864.55   703.1 1879.13   762.5 1911.16
   772.4 1918.28   782.3 1929.51   851.6 1976.46   861.5  1989.1   920.9 2031.27
   940.7 2051.38  1000.2 2093.15  1069.5 2163.85  1089.3 2176.86  1099.2 2187.44
#Mann= 3 , 0 , 0
       0      .1       0   495.2    .045       0   505.1      .1       0
Bank Sta=495.2,505.1
XS Rating Curve= 0 ,0
Exp/Cntr=0.3,0.1

Type RM Length L Ch R = 1 ,3389.2  ,300.3,299.9,295.8
XS GIS Cut Line= 3
     1867817.039      251365.356     1867273.494      251347.563
     1866716.036      251370.983
#Sta/Elev= 30
       0 2001.86    59.3 1976.52    69.2 1968.29   138.4 1946.37   148.3 1940.75
   197.8 1928.09   217.5 1925.99   257.1 1911.78   296.6 1895.44   306.5 1887.37
   316.4 1881.56   365.8 1860.43   454.8 1833.82   474.6 1824.74   514.2 1812.15
     534 1807.82   536.3 1807.91   551.3 1808.93   623.5 1813.36   643.5 1817.46
   693.3 1837.06   703.2 1841.33   713.2 1848.14     773 1873.12   792.9 1885.27
   852.7 1912.27   872.6  1925.8   892.6 1932.95    1032 1959.28  1101.8 1965.18
#Mann= 3 , 0 , 0
       0      .1       0   536.3    .045       0   551.3      .1       0
Bank Sta=536.3,551.3
XS Rating Curve= 0 ,0
Exp/Cntr=0.3,0.1

Type RM Length L Ch R = 1 ,3089.2  ,291.5,290,282.6
XS GIS Cut Line= 3
     1867783.993      251063.786      1867233.66      251058.549
     1866679.015      251176.456
#Sta/Elev= 30
       0 2115.05      30 2102.14      50 2087.78   110.1 2052.46   130.1 2035.41
   190.1 2002.46   210.1 1984.51   270.2 1948.78   290.2 1933.06   350.2 1900.36
   370.2 1883.69   430.3 1850.16   450.3 1831.29   460.3  1825.2   480.3 1814.86
   500.3 1808.07   542.9 1801.86   550.4 1801.75   557.9 1801.99   679.7 1808.55
   699.6 1815.43   759.3 1828.82     819 1846.52   858.8 1861.92   958.2  1892.6
     998 1908.74    1008 1917.72  1077.6 1942.58  1087.6 1949.28  1117.4 1957.92
#Mann= 3 , 0 , 0
       0      .1       0   542.9    .045       0   557.9      .1       0
Bank Sta=542.9,557.9
XS Rating Curve= 0 ,0
Exp/Cntr=0.3,0.1

Type RM Length L Ch R = 1 ,2799.2  ,239.3,251.7,275.4
XS GIS Cut Line= 3
     1867723.443      250686.075     1867137.787      250800.525
     1866656.824      251095.995
#Sta/Elev= 30
       0 2056.22    59.7 2041.21    79.6 2031.65   149.2 2008.97   228.8 1973.01
   238.7 1963.26   308.3 1928.23   328.2 1911.69   387.9 1878.47   407.8 1861.33
   467.4  1826.8   487.3 1808.66   497.3 1803.52   527.1 1796.19   586.8 1795.91
   589.2 1795.95   604.2 1796.58   685.9 1801.13   705.7 1805.36   725.5  1813.7
   735.4 1823.53     775 1846.64   834.4 1876.76   913.6 1895.61   923.5 1903.22
  1002.8 1943.65  1022.6 1956.87  1101.8 1981.63  1111.7 1986.95  1161.2 1992.39
#Mann= 3 , 0 , 0
       0      .1       0   589.2    .045       0   604.2      .1       0
Bank Sta=589.2,604.2
XS Rating Curve= 0 ,0
Exp/Cntr=0.3,0.1

Type RM Length L Ch R = 1 ,2547.1  ,347.1,335.2,323.4
XS GIS Cut Line= 3
     1867722.309       250625.02     1867231.737      250637.571
     1866639.389      250332.218
#Sta/Elev= 30
       0 2018.93    58.9 1998.58    78.5 1987.68   137.4 1972.08   215.9 1942.35
   235.6 1930.87   304.2 1902.66   314.1 1894.57     373 1867.98   382.8 1861.73
   392.6 1849.88   412.2 1836.11   480.9 1800.98   510.6 1793.17   573.4 1790.75
   588.4 1790.63   590.2 1790.62   639.9 1794.63   659.8  1799.3   699.6 1815.57
   739.4 1824.67   759.3  1833.4   828.9 1854.44   848.8 1867.12   918.4 1899.33
  1027.8 1975.55  1057.7  1987.1  1097.5 2007.82  1127.3 2028.96  1157.2 2041.14
#Mann= 3 , 0 , 0
       0     .06       0   573.4    .045       0   588.4     .06       0
Bank Sta=573.4,588.4
XS Rating Curve= 0 ,0
Exp/Cntr=0.3,0.1

Type RM Length L Ch R = 1 ,2211.8  ,304.9,305.1,305.3
XS GIS Cut Line= 3
     1867745.912      250293.699     1867200.789      250305.776
     1866653.822      250246.122
#Sta/Elev= 30
       0 2077.26    29.7 2057.76    39.7 2046.84     109 2006.42     119 1996.03
   188.4 1956.84   198.3 1946.06   267.7 1909.36   277.6 1899.12   406.5  1842.2
   416.4 1836.68   426.3 1826.21   436.2 1819.59   495.7 1785.15   502.6 1783.61
   505.6 1782.94   517.6 1783.77   585.3  1788.3   655.3 1797.12   735.3 1819.43
   755.3 1830.84   805.4 1850.85   835.4 1871.56   895.4 1900.68   915.4 1915.54
   975.4 1950.76   995.4 1967.99  1055.4 2001.84  1075.5 2018.92  1095.5  2030.1
#Mann= 3 , 0 , 0
       0     .06       0   502.6    .045       0   517.6     .06       0
Bank Sta=502.6,517.6
XS Rating Curve= 0 ,0
Exp/Cntr=0.3,0.1

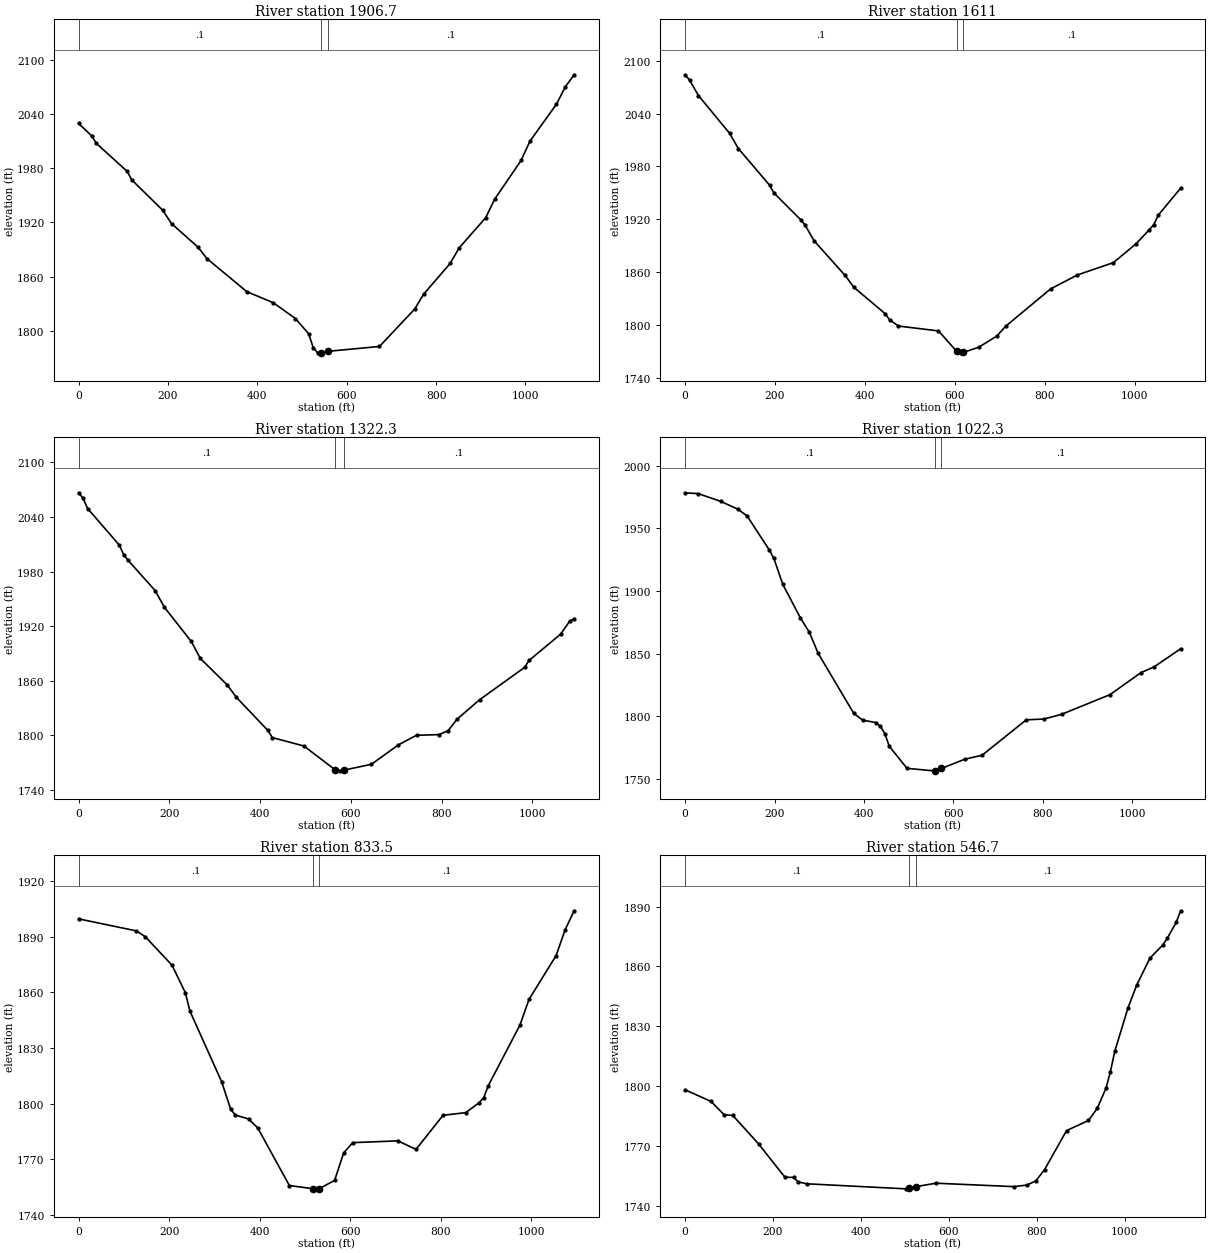
Type RM Length L Ch R = 1 ,1906.7  ,288.7,295.7,302.7
XS GIS Cut Line= 3
      1867745.07      250083.321     1867388.375      249999.945
     1866645.682      250008.631
#Sta/Elev= 30
       0 2029.62    29.7 2015.65    39.6 2007.56   108.9 1976.41   118.8 1967.17
   188.1 1933.45   207.9 1918.68   267.3  1892.5   287.1 1879.93   376.2 1843.33
   435.6 1830.98   485.2  1813.5   514.9 1796.55   524.8 1781.37   534.7 1775.66
   542.6 1775.52   544.6 1775.48   557.6 1777.14   673.3 1782.55   752.5 1824.24
   772.3 1840.59   831.8 1874.74   851.6 1891.77     911 1925.22   930.8 1945.52
   990.2  1988.6    1010    2010  1069.4 2051.02  1089.2 2070.29    1109 2083.56
#Mann= 3 , 0 , 0
       0      .1       0   542.6    .045       0   557.6      .1       0
Bank Sta=542.6,557.6
XS Rating Curve= 0 ,0
Exp/Cntr=0.3,0.1

Type RM Length L Ch R = 1 ,1611    ,291.6,288.7,285.8
XS GIS Cut Line= 3
     1867803.407      249921.402     1867294.227      249730.522
     1866759.954      249567.598
#Sta/Elev= 30
       0 2083.95     9.9 2077.94    29.7  2060.4    98.9 2017.59   118.6 2000.25
   187.8 1958.81   197.7 1949.85   257.1 1919.55     267 1913.43   286.7 1895.82
   355.9 1856.38   375.7  1842.8   444.9 1813.02   454.8 1806.14   474.6 1798.96
   563.7 1793.44   603.9 1770.48   613.6 1768.58   618.9 1769.04   653.5 1775.01
   693.4 1787.59   713.4 1798.86   813.1  1841.1   872.9 1856.92   952.7 1870.88
  1002.6 1891.95  1032.5 1908.09  1042.5 1913.79  1052.5 1924.57  1102.4 1955.42
#Mann= 3 , 0 , 0
       0      .1       0   603.9    .045       0   618.9      .1       0
Bank Sta=603.9,618.9
XS Rating Curve= 0 ,0
Exp/Cntr=0.3,0.1

Type RM Length L Ch R = 1 ,1322.3  ,300.5,299.9,297
XS GIS Cut Line= 3
     1867867.569      249526.511     1867329.284       249435.05
      1866790.87      249344.349
#Sta/Elev= 30
       0 2066.53     9.9 2060.45    19.8 2049.25    89.4 2009.21    99.3 1998.58
   109.2 1992.19   168.8 1959.05   188.6 1941.02   248.2 1903.25     268  1884.7
   327.6 1855.42   347.4 1841.98     417  1805.5   426.9 1797.65   496.4  1788.4
   565.8 1762.07   575.8 1761.13   585.3 1761.96   645.3 1768.33   704.8  1789.7
   744.6 1800.17   794.2 1800.91     814 1805.16   833.9 1817.81   883.5  1839.2
   982.8 1874.77   992.7 1882.44  1062.2 1911.28  1082.1 1925.44    1092 1928.29
#Mann= 3 , 0 , 0
       0      .1       0   565.8    .045       0   585.3      .1       0
Bank Sta=565.8,585.3
XS Rating Curve= 0 ,0
Exp/Cntr=0.3,0.1

Type RM Length L Ch R = 1 ,1022.3  ,186.7,188.8,193.2
XS GIS Cut Line= 3
     1867889.414      249219.505     1867329.463      249137.758
      1866787.38      249116.728
#Sta/Elev= 30
       0 1978.51    29.8  1977.8    79.4  1971.7   119.1 1965.22     139 1959.86
   188.6  1932.7   198.6 1926.07   218.4  1905.5   258.1 1878.48     278 1867.08
   297.8  1850.2   377.3 1802.37   397.1 1797.01   426.9 1795.04   436.8 1791.95
   446.8 1786.32   456.7  1776.1   496.4 1758.52     556 1756.52   558.4  1756.7
   573.4 1758.41   625.1 1765.74   664.5 1769.01   763.2 1797.26   802.6 1797.87
   842.1 1801.65   950.6 1817.38  1019.6 1834.92  1049.2 1839.53  1108.4    1854
#Mann= 3 , 0 , 0
       0      .1       0   558.4    .045       0   573.4      .1       0
Bank Sta=558.4,573.4
XS Rating Curve= 0 ,0
Exp/Cntr=0.3,0.1

Type RM Length L Ch R = 1 ,833.5   ,285.3,286.9,288.4
XS GIS Cut Line= 3
     1867908.919      249087.016     1867688.993      249034.803
     1866844.568      248828.731
#Sta/Elev= 30
       0 1899.68   127.8 1893.19   147.4 1890.04   206.4 1874.66     236 1859.77
     246  1849.9     316 1811.82   335.9 1797.11   345.9 1793.85   375.9 1791.69
   395.9 1786.84   465.8 1755.78   517.1  1754.1   525.8    1754   532.1 1754.14
   565.7 1758.54   585.7 1773.33   605.7 1778.93   705.6 1779.89   745.6 1775.28
   805.5 1793.69   855.5 1795.12   885.4 1800.49   895.4 1803.22   905.4 1809.68
   975.4 1842.41   995.3 1856.19  1055.3 1879.89  1075.3 1893.86  1095.2 1904.05
#Mann= 3 , 0 , 0
       0      .1       0   517.1    .045       0   532.1      .1       0
Bank Sta=517.1,532.1
XS Rating Curve= 0 ,0
Exp/Cntr=0.3,0.1

Type RM Length L Ch R = 1 ,546.7   ,559,546.3,533.5
XS GIS Cut Line= 4
      1867874.11      248962.022      1867614.63      248734.186
     1867248.181      248624.519      1866874.16      248764.247
#Sta/Elev= 30
       0 1798.26    59.2 1792.39    88.8 1785.76   108.5 1785.42   167.7 1771.01
   226.9 1754.51   246.6 1754.39   256.5 1752.22   276.2  1751.2   502.2 1748.67
   509.8 1748.89   524.8 1749.78   570.9 1751.49   747.8 1749.78   777.7 1750.57
   797.7 1752.64   817.6 1758.27   867.6 1777.83   917.5 1782.89   937.4 1788.95
   957.4 1799.07   967.4  1807.4   977.4 1817.55  1007.3 1839.21  1027.3 1850.71
  1057.2 1864.15  1087.2 1870.88  1097.1 1874.22  1117.1 1882.14  1127.1 1887.86
#Mann= 3 , 0 , 0
       0      .1       0   509.8    .045       0   524.8      .1       0
Bank Sta=509.8,524.8
XS Rating Curve= 0 ,0
Exp/Cntr=0.3,0.1

Chan Stop Cuts=-1
Use User Specified Reach Order=0
Composite Channel Slope=5